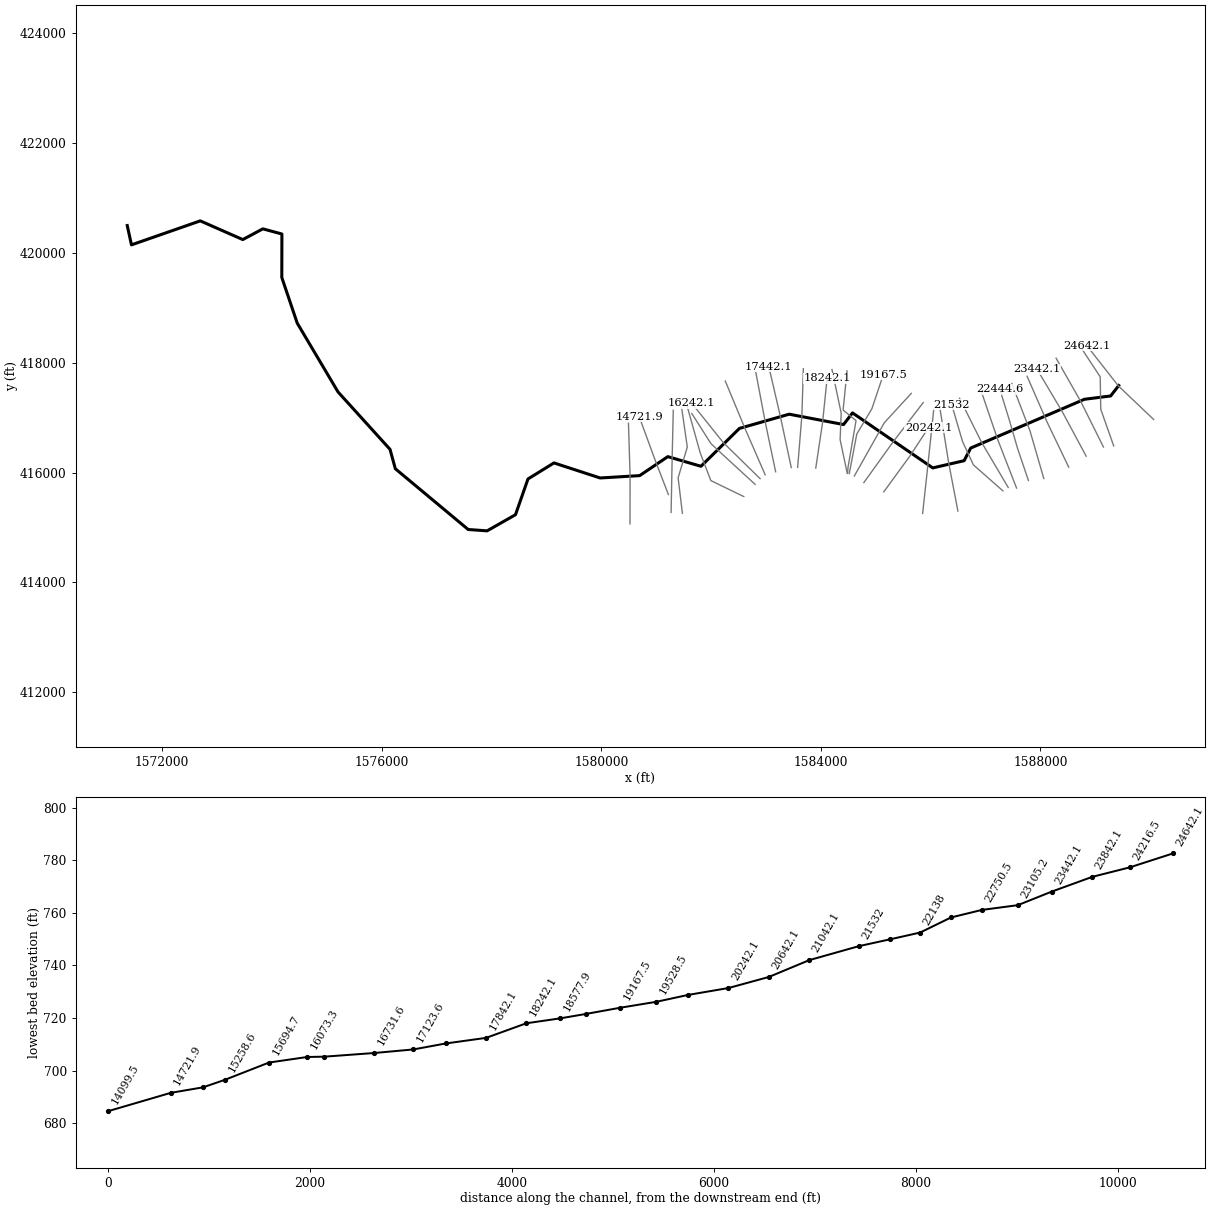
--- LAURELCR.prj (project) ---

Proj Title=LAURELCR
Current Plan=p01
Default Exp/Contr=0,0
English Units
Geom File=g01
Flow File=f01
Plan File=p01
BEGIN DESCRIPTION:
END DESCRIPTION:
DSS Export Rating Curves= 0
DSS Export Rating Curve Sorted= 0
DSS Export Volume Flow Curves= 0
DXF OffsetX= 0
DXF OffsetY= 0
DXF ScaleX= 0
DXF ScaleY= 0

--- LAURELCR.p01 (plan) ---

Plan Title=Floodplain
Program Version=4.00
Geom File=g01
Flow File=f01
K Sum by GR=0
Std Step Tol=0.01
Critical Tol=0.01
Num of Std Step Trials=20
Max Error Tol=0.3
Flow Tol Ratio=0.001
Split Flow NTrial=30
Split Flow Tol=0.02
Split Flow Ratio=0.02
Log Output Level=0
Friction Slope Method=1
Unsteady Friction Slope Method=2
Unsteady Bridges Friction Slope Method=1
Global Log Level=0
CheckData=False
Run HTab=0
Run UNet=0
Run PostProcess=0
UNET Theta=0
UNET Theta Warmup=0
UNET ZTol=0
UNET ZSATol=0
UNET MxIter=0
UNET MaxInSteps=0
UNET DtIC=0
UNET DtMin=0
UNET MaxCRTS=0
UNET WFStab=0
UNET SFStab=0
UNET WFX=0
UNET SFX=0
UNET DSS MLevel=0
UNET DZMax Abort=0
UNET Convert EG Bridges=0
UNET Use Existing IB Tables=0
UNET Froude Limit=0
UNET Froude Power=0
Write IC File=0
Echo Input=False
Echo Output=False
Write Detailed=0

--- LAURELCR.f01 (steady flow) ---

Flow Title=NFF Regression Equation
Program Version=4.00
Number of Profiles= 1
Profile Names=P100yr
River Rch & RM=LAURELCR,Main            ,24642.1
     358
River Rch & RM=LAURELCR,Main            ,22750.5
     389
River Rch & RM=LAURELCR,Main            ,22138
     432
River Rch & RM=LAURELCR,Main            ,20642.1
     467
River Rch & RM=LAURELCR,Main            ,18831.1
     501
River Rch & RM=LAURELCR,Main            ,18577.9
     661
River Rch & RM=LAURELCR,Main            ,18242.1
     666
River Rch & RM=LAURELCR,Main            ,16731.6
     738
River Rch & RM=LAURELCR,Main            ,15258.6
     806
River Rch & RM=LAURELCR,Main            ,11958.4
     886
Boundary for River Rch & Prof#=LAURELCR,Main            , 1
Up Type= 0
Dn Type= 3
Dn Slope=0.005189
DSS Import GetInterval= 0
DSS Import GetPeak= 0
DSS Import FillOption= 0

--- LAURELCR.g01 (geometry) ---

Geom Title=USGS 10m DEM
Program Version=4.00

River Reach=LAURELCR        ,Main
Reach XY= 30
     1589426.067      417585.885      1589278.47      417395.737
      1588800.69      417335.201     1586729.327      416447.324
     1586609.194      416217.115     1586038.321      416085.922
     1584575.727      417087.665     1584413.259      416875.352
     1583422.149      417063.769     1582516.577      416805.071
     1581815.987      416115.647     1581211.927      416291.024
     1580699.581       415945.54     1579978.639       415902.62
      1579138.06      416176.671     1578664.701      415884.381
     1578437.123      415233.491     1577920.369      414940.018
     1577575.791        414964.3     1576248.834      416070.253
     1576151.574       416424.07     1575205.427      417467.941
     1574461.639       418721.74     1574180.537      419552.405
     1574182.329      420344.758     1573834.849      420438.426
     1573469.731      420243.039     1572695.572      420583.712
     1571442.195      420146.978     1571364.991      420498.472

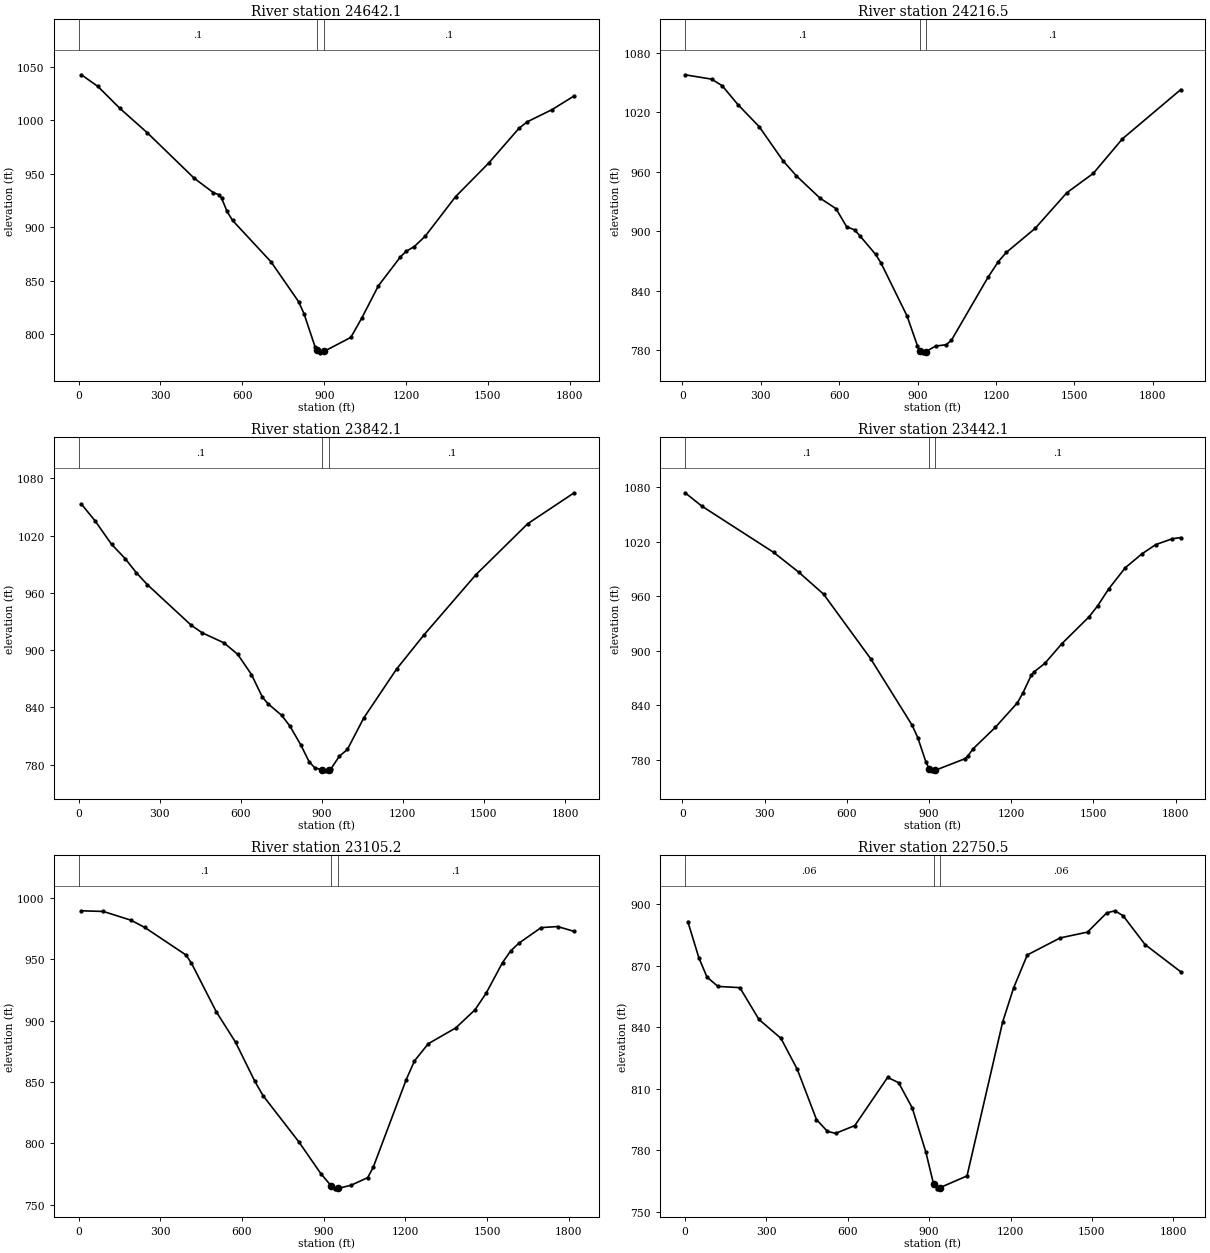
Type RM Length L Ch R = 1 ,24642.1 ,447.5,425.6,407.8
XS GIS Cut Line= 3
     1590061.771      416967.413     1589419.512      417578.334
     1588846.294       418310.23
#Sta/Elev= 30
    10.1 1042.42    70.5 1031.56   151.1 1011.04   251.8   988.2   423.1  945.84
   493.6  932.33   513.7  930.34   523.8  927.19   543.9  914.77   564.1  906.31
   705.1  867.61   805.8  830.52     826   819.1   866.3  788.35   873.9  785.06
   886.4  782.56   898.9  783.85   997.6  796.97    1038  815.21  1098.6  845.23
  1179.5  872.25  1199.7  877.36    1230  881.83  1270.4  891.62  1381.5  928.54
  1502.8  959.88    1614  992.45  1644.3  998.49  1735.2 1009.88  1816.1 1022.68
#Mann= 3 , 0 , 0
       0      .1       0   873.9    .045       0   898.9      .1       0
Bank Sta=873.9,898.9
XS Rating Curve= 0 ,0
Exp/Cntr=0.3,0.1

Type RM Length L Ch R = 1 ,24216.5 ,362.1,374.4,388.2
XS GIS Cut Line= 4
     1589334.202      416485.645     1589098.234      417154.222
     1589088.402      417744.142     1588754.699      418251.519
#Sta/Elev= 30
    10.1 1057.93   111.4 1053.53   151.9 1046.93   212.7  1027.7   293.7 1005.56
   384.9   971.1   435.5  956.04   526.7  933.35   587.5  922.82     628  904.62
   658.4  901.39   678.6   895.5     739  876.69     759  868.35     859  814.72
     899  784.57     909     779     919  777.28   931.5  778.57     969  784.14
    1009  785.45    1029  789.89    1169  853.44    1209  869.45    1239  878.56
  1349.6  902.91  1471.1  938.94  1572.3  958.47  1683.6   993.3  1906.3 1042.88
#Mann= 3 , 0 , 0
    10.1      .1       0     909    .045       0   931.5      .1       0
Bank Sta=909,931.5
XS Rating Curve= 0 ,0
Exp/Cntr=0.3,0.1

Type RM Length L Ch R = 1 ,23842.1 ,401.5,400,398.3
XS GIS Cut Line= 3
     1589147.394      416465.981     1588735.429      417292.859
     1588284.859      418083.601
#Sta/Elev= 30
    10.2 1052.92    60.9 1035.35   121.8 1010.84   172.6  995.73   213.2  981.17
   253.8  968.71   416.2   926.2   456.8  918.23     538  907.61   588.8  895.59
   639.6  874.49   680.2   850.7   700.5  844.02   751.2  831.78   781.7  820.57
   822.3  800.75   852.8  783.29   873.1  777.03   901.2   774.4   913.7  773.64
   926.2  774.15   933.9  775.75   964.3  788.75   994.6  796.04  1055.3  829.03
  1176.6   880.2  1277.7  915.86  1469.9  978.86    1662 1032.36  1833.9 1064.75
#Mann= 3 , 0 , 0
       0      .1       0   901.2    .045       0   926.2      .1       0
Bank Sta=901.2,926.2
XS Rating Curve= 0 ,0
Exp/Cntr=0.3,0.1

Type RM Length L Ch R = 1 ,23442.1 ,336.8,336.9,335.7
XS GIS Cut Line= 3
      1588832.77      416298.837     1588402.179      417100.293
     1587938.057       417881.79
#Sta/Elev= 30
    10.1  1073.6    70.8 1059.02   333.6 1008.04   424.6  986.42   515.6  962.18
   687.4  891.25     839  818.02   859.3  804.51   889.6  777.27  901.42  770.22
   909.8  768.05   922.3  768.57    1031  781.29  1041.1  783.93  1061.3  792.29
  1142.1  815.76  1222.9  842.82  1243.1  853.73  1273.4  873.05  1283.5   876.7
  1323.9  886.38  1384.5  907.56  1485.5   937.6  1515.8  949.39  1556.1  967.91
  1616.7  991.26  1677.3 1006.45  1727.8 1016.65  1788.4 1023.08  1818.7 1024.37
#Mann= 3 , 0 , 0
    10.1      .1       0  901.42    .045       0   922.3      .1       0
Bank Sta=901.42,922.3
XS Rating Curve= 0 ,0
Exp/Cntr=0.3,0.1

Type RM Length L Ch R = 1 ,23105.2 ,356.9,354.8,353.6
XS GIS Cut Line= 3
     1588514.385      416099.656     1588120.683       416920.21
     1587756.337      417754.277
#Sta/Elev= 30
    10.1  989.58      91  989.02   192.1   981.9   242.7  976.02   394.4  953.53
   414.6  946.81   505.6  907.27   576.4  882.42   647.2  850.58   677.5  838.84
     809  801.16   889.9  775.24     928  765.22   940.5  762.88     953  763.24
  1001.1  765.83  1061.8  772.03    1082  780.39  1203.4  851.96  1233.7  867.21
  1284.3  881.18  1385.4  894.09  1456.2  908.91  1496.7  922.31  1557.3   947.4
  1587.7  957.03    1618  963.28  1698.9  975.86  1759.6  976.72  1820.3  972.78
#Mann= 3 , 0 , 0
       0      .1       0     928    .045       0     953      .1       0
Bank Sta=928,953
XS Rating Curve= 0 ,0
Exp/Cntr=0.3,0.1

Type RM Length L Ch R = 1 ,22750.5 ,307.1,305.9,303.6
XS GIS Cut Line= 3
     1588061.232      415891.617     1587807.995       416764.01
     1587478.457      417621.936
#Sta/Elev= 30
    10.1  891.53    50.5  873.97    80.7  864.44   121.1  859.89   201.9  859.29
   272.5  843.74   353.3  834.58   413.8  819.38   484.5  794.92   524.9  789.11
   555.1  788.18   625.8  791.95   746.9  815.49   787.3   812.9   837.8  800.53
   888.2  778.83   916.1  763.51   928.6  761.08   941.1  761.73  1039.7  767.39
    1171   842.5  1211.4  859.14  1261.9  875.25  1383.1  883.56  1484.1  886.41
  1554.8  895.78  1585.1  896.81  1615.4  894.36  1696.2  880.32  1827.4  867.06
#Mann= 3 , 0 , 0
       0     .06       0   916.1    .045       0   941.1     .06       0
Bank Sta=916.1,941.1
XS Rating Curve= 0 ,0
Exp/Cntr=0.3,0.1

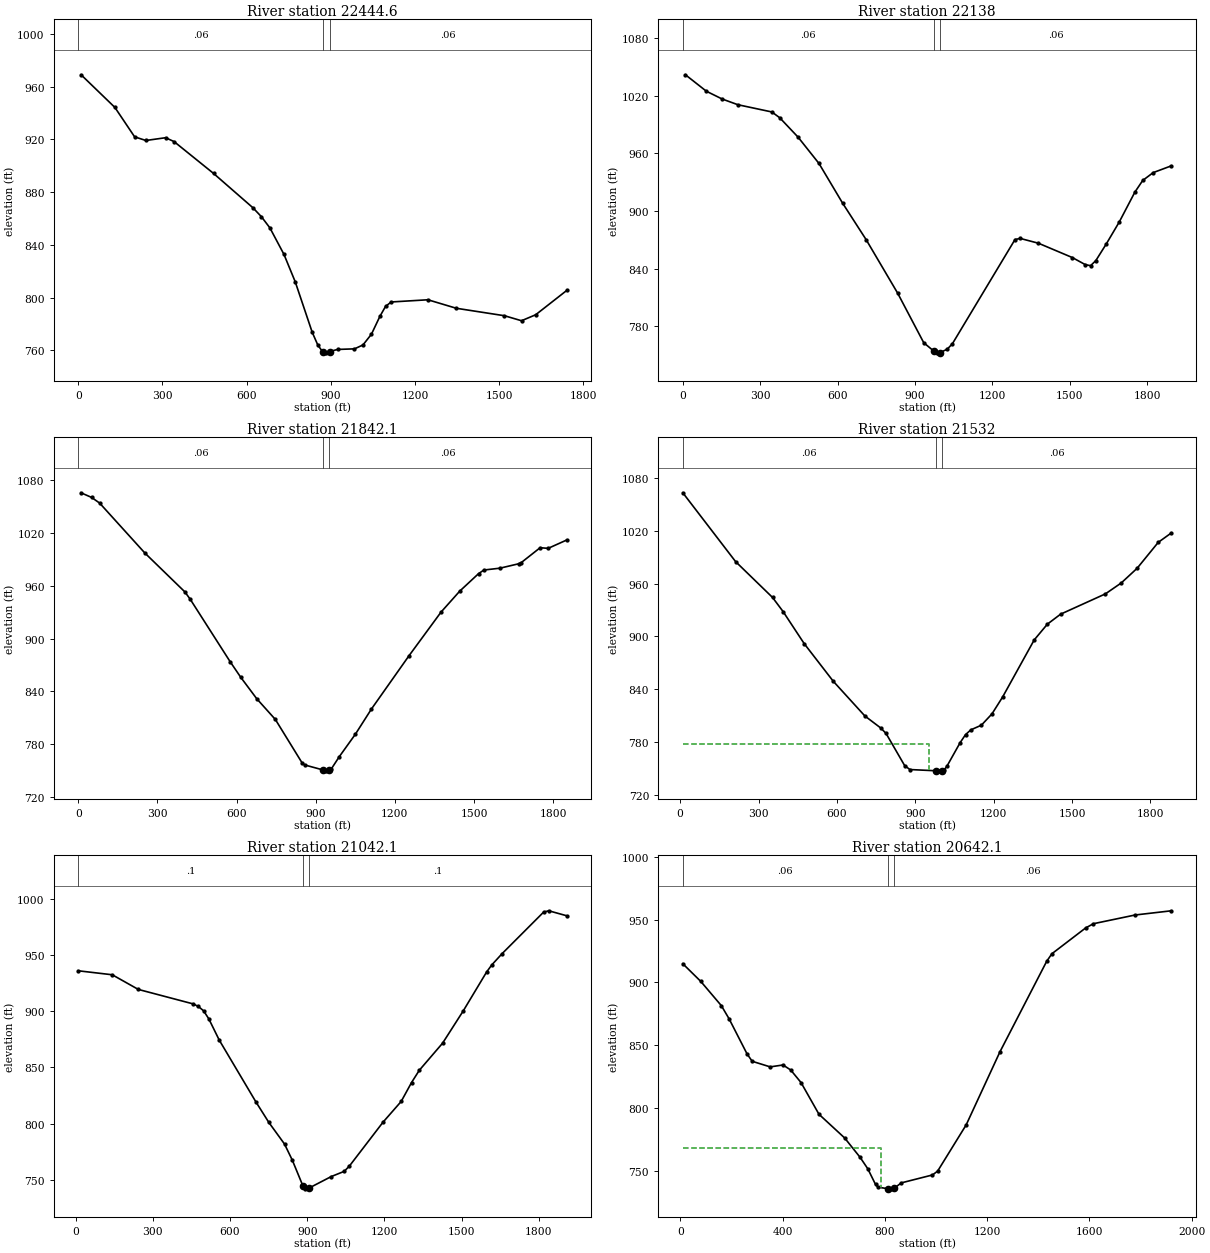
Type RM Length L Ch R = 1 ,22444.6 ,305.4,306.6,307.9
XS GIS Cut Line= 4
     1587780.745      415856.397     1587584.105      416436.485
     1587426.793      416977.245     1587259.649      417518.006
#Sta/Elev= 30
      10  968.96   130.5  944.21   200.8  921.92     241  919.16   311.3  921.26
   341.4  918.33     482  894.22   622.6  868.15   652.7  861.41   682.9  852.97
   733.2  832.82   773.4  812.02   833.8  773.84   853.9  764.09   871.5  758.87
     884  758.21   896.5  759.22   924.3  760.79   984.6  761.23  1014.8  764.19
    1045  772.33  1075.1  785.84  1095.2  793.37  1115.3  796.76  1246.4  798.43
  1347.5  791.99  1519.3  786.33    1580  782.54  1630.5  787.08  1741.7  805.59
#Mann= 3 , 0 , 0
       0     .06       0   871.5    .045       0   896.5     .06       0
Bank Sta=871.5,896.5
XS Rating Curve= 0 ,0
Exp/Cntr=0.3,0.1

Type RM Length L Ch R = 1 ,22138   ,290.2,295.8,299.6
XS GIS Cut Line= 3
     1587564.441      415718.749     1587222.315      416598.996
     1586915.528      417498.342
#Sta/Elev= 30
    10.2 1041.77    91.4 1024.65   152.3 1016.59   213.3 1010.63   345.3 1003.08
   375.7  997.08   446.8  976.92     528   949.5   619.4  908.29   710.8  870.26
   832.7  814.74   934.2  762.99   972.3  754.49   984.8  752.46   997.3  752.72
  1025.3  756.24  1045.5  761.98  1288.1  870.35  1308.3  871.51  1379.1  866.49
  1510.5  851.59    1561  844.18  1581.3  843.17  1601.5  848.43  1641.9   865.7
  1692.5  888.67  1753.1  919.76  1783.4  931.83  1823.9  939.98  1894.6  947.06
#Mann= 3 , 0 , 0
       0     .06       0   972.3    .045       0   997.3     .06       0
Bank Sta=972.3,997.3
XS Rating Curve= 0 ,0
Exp/Cntr=0.3,0.1

Type RM Length L Ch R = 1 ,21842.1 ,313.4,310.2,309
XS GIS Cut Line= 3
     1587412.663      415728.957     1586930.503      416546.362
     1586526.079      417353.863
#Sta/Elev= 30
    10.1 1065.32    50.5 1060.05    80.8 1053.66   252.4  996.98   403.8  952.96
     424   944.7   575.5  873.78   615.8  856.04   676.4  831.74   747.1  808.16
   848.1  759.06   858.2  756.58   926.4  751.03   938.9  749.91   951.4  750.47
   959.2  752.14   989.6  766.08  1050.5  791.52  1111.4  820.12  1253.4  880.38
  1375.2  930.03  1446.2  953.83  1517.3  973.59  1537.6   977.7  1598.4  979.79
  1669.5   984.8  1679.6  986.22  1750.7    1003  1781.1 1002.29  1852.1 1011.83
#Mann= 3 , 0 , 0
       0     .06       0   926.4    .045       0   951.4     .06       0
Bank Sta=926.4,951.4
XS Rating Curve= 0 ,0
Exp/Cntr=0.3,0.1

Type RM Length L Ch R = 1 ,21532   ,497.1,489.8,481.7
XS GIS Cut Line= 4
     1587316.171      415667.815      1586777.88      416141.525
      1586581.24      416564.301       1586384.6      417232.878
#Sta/Elev= 30
    10.1 1063.25   212.1  985.05   353.5  944.32   393.9  928.28   474.7  891.83
   585.8  849.14   706.9  809.65   767.7  795.98     788  789.79     859  753.35
   879.2  748.77   978.2  747.39   990.7   747.3  1003.2  747.64    1011  748.65
  1021.1  752.61  1071.8  779.45  1092.1   788.4  1112.4  793.85  1152.9  799.18
  1193.4  812.02  1233.8  831.03    1355  896.03  1405.5  913.98    1456   925.3
  1627.7   948.4  1688.3   960.8  1748.9  977.45  1829.7  1006.9  1880.2 1017.68
#Mann= 3 , 0 , 0
    10.1     .06       0   978.2    .045       0  1003.2     .06       0
#XS Ineff= 2 , 0
          951.19  778.28
Permanent Ineff=
       F       F
Bank Sta=978.2,1003.2
XS Rating Curve= 0 ,0
Exp/Cntr=0.3,0.1

Type RM Length L Ch R = 1 ,21042.1 ,408.3,400,392.6
XS GIS Cut Line= 3
     1586496.124      415300.486     1586328.245      416177.496
     1586166.824      417181.241
#Sta/Elev= 30
    10.1  936.08   142.1  932.54   243.5  919.49   456.6  906.61   476.9  904.32
   497.2  900.47   517.5  893.31   558.1  874.39   700.1  819.57   750.9  801.11
   811.8  781.89   842.2  767.51  883.68  744.44   892.9     742   905.4  742.48
   993.6  752.94  1043.9  757.56  1064.1  762.29  1194.9  801.35  1265.4  819.78
  1305.6  836.58  1335.8  847.51  1426.4  871.66  1506.9  900.46  1597.5  934.99
  1617.7  941.33  1657.9  951.37    1819  988.28  1839.1  989.49  1909.6  985.01
#Mann= 3 , 0 , 0
    10.1      .1       0  883.68    .045       0   905.4      .1       0
Bank Sta=883.68,905.4
XS Rating Curve= 0 ,0
Exp/Cntr=0.3,0.1

Type RM Length L Ch R = 1 ,20642.1 ,414.4,400,386.9
XS GIS Cut Line= 3
     1585853.672      415256.644     1585943.805      416085.567
     1586057.709      417166.368
#Sta/Elev= 30
      10  914.89    80.4  900.78   160.7   881.5   190.9  871.05   261.2  843.07
   281.3  837.19   351.6  832.74   401.8  834.25     432  830.25   472.2  820.27
   542.5  794.98   642.9  776.11   703.2  760.71   733.4  751.56   763.5  739.13
   773.5  736.94   811.3  735.71   823.8   735.6   836.3  736.06   864.3  740.34
   986.2  746.65  1006.5  749.74  1118.2  786.59  1250.2  844.77  1433.1  916.91
  1453.4  922.87  1585.4  943.43  1615.9  946.78  1778.4   953.7  1920.6  957.07
#Mann= 3 , 0 , 0
      10     .06       0   811.3    .045       0   836.3     .06       0
#XS Ineff= 2 , 0
          785.11  768.23
Permanent Ineff=
       F       F
Bank Sta=811.3,836.3
XS Rating Curve= 0 ,0
Exp/Cntr=0.3,0.1

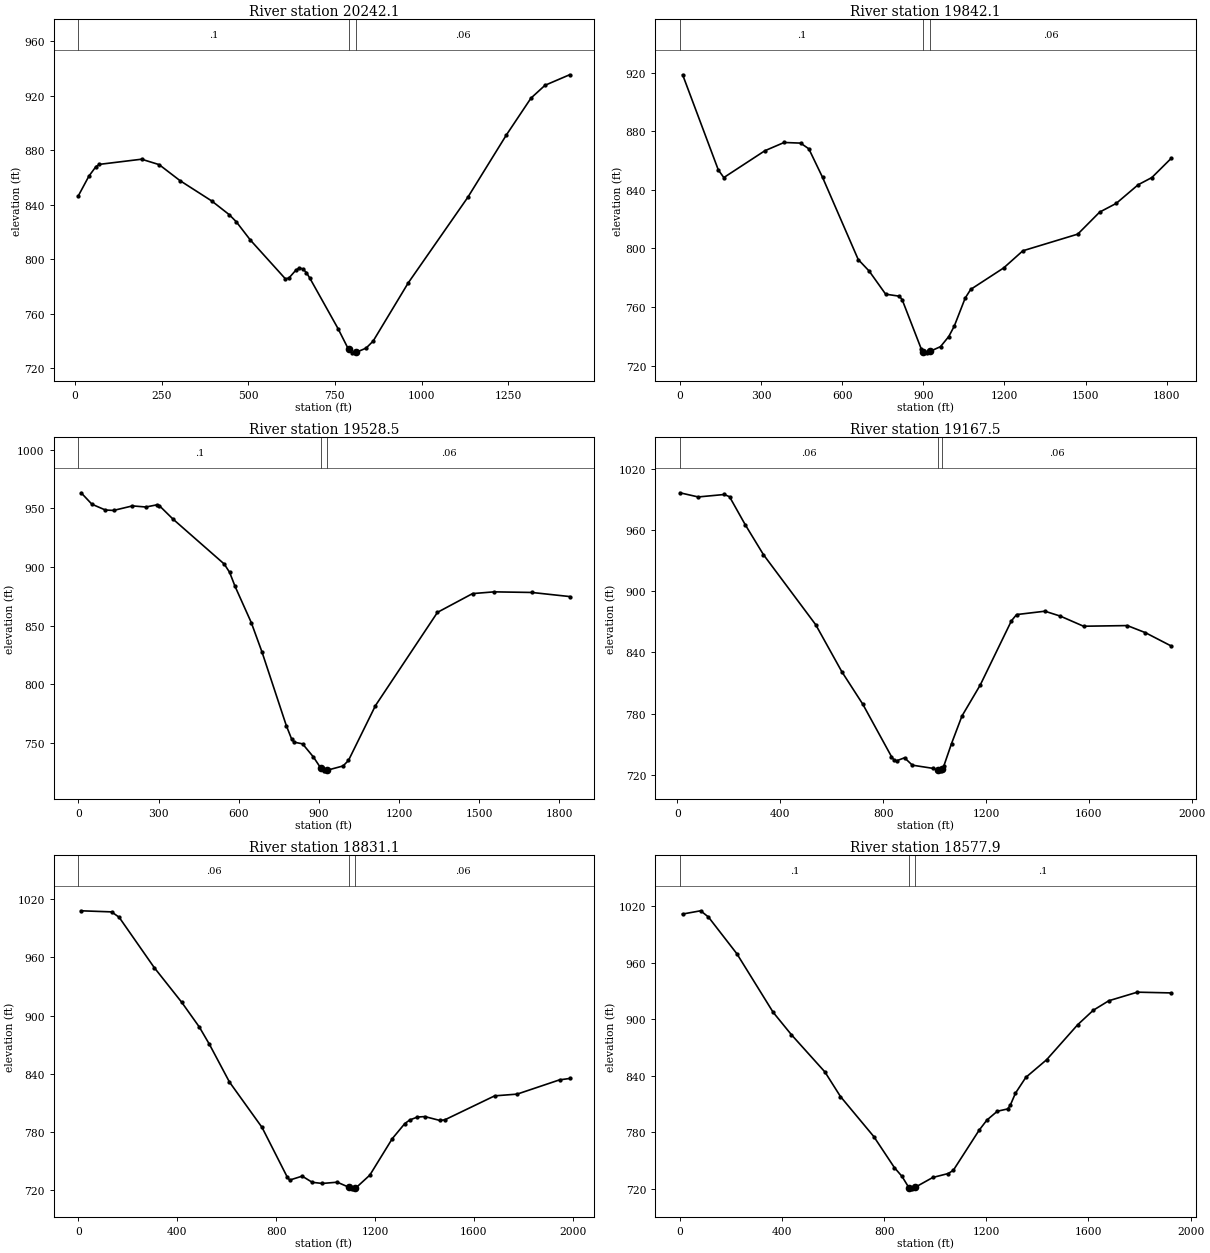
Type RM Length L Ch R = 1 ,20242.1 ,399.8,400,398
XS GIS Cut Line= 3
     1585145.767      415649.925     1585617.101       416295.65
     1585961.824      416819.933
#Sta/Elev= 30
    10.1  846.71    40.5  861.11    60.7  868.04    70.8  869.69   192.3  873.47
   242.9   869.5   303.6  857.67   394.7  842.83   445.3  832.75   465.5  827.57
     506  814.19   607.2  785.68   617.3  786.27   637.5  792.08   647.7  793.71
   657.8  792.88   667.9  790.25     678  786.04     759  749.18   789.3  733.93
   799.4  731.39   811.9   731.8   839.9  734.85   860.2  739.97   961.4  782.66
  1133.4  845.52  1244.7  891.28  1315.6  918.29  1356.1  927.71  1426.9  935.42
#Mann= 3 , 0 , 0
    10.1      .1       0   789.3    .045       0   811.9     .06       0
Bank Sta=789.3,811.9
XS Rating Curve= 0 ,0
Exp/Cntr=0.3,0.1

Type RM Length L Ch R = 1 ,19842.1 ,310.6,313.6,317.5
XS GIS Cut Line= 3
     1584781.983      415817.069     1585308.681      416550.186
     1585864.268      417275.205
#Sta/Elev= 30
    10.1  918.54     142  853.58   162.3  848.39   314.4  866.73   385.4  872.34
   446.3   871.9   476.7     868   527.4  848.53   659.3  792.45   699.8  784.57
   760.7  768.81   811.4  767.43   821.6  765.14   892.6  731.32   900.4  729.48
   912.9  728.77   925.4  729.82   963.6  733.01     994  739.88  1014.3  746.93
  1054.9  766.18  1075.2  772.07    1197   786.7  1268.1  798.42  1471.1  809.79
  1552.2  824.84  1613.1  830.74  1694.3  843.47  1745.1  848.41  1816.1  861.43
#Mann= 3 , 0 , 0
       0      .1       0   900.4    .045       0   925.4     .06       0
Bank Sta=900.4,925.4
XS Rating Curve= 0 ,0
Exp/Cntr=0.3,0.1

Type RM Length L Ch R = 1 ,19528.5 ,361.6,361,359.7
XS GIS Cut Line= 3
     1584609.986      415939.474     1585155.599      416908.421
     1585647.449      417443.112
#Sta/Elev= 30
    10.1   963.4    50.5  953.65   101.1  948.68   131.4  948.34   202.2   952.2
   252.7  951.26   293.2  953.09   303.3  952.32   353.8  941.01   545.9   902.6
   566.1  895.48   586.3  883.56     647   852.7   687.4  827.42   778.4  764.63
   798.6  753.02   808.7  750.59   839.1  749.17   879.5  738.03   907.4  728.46
   919.9  726.16   932.4  726.77   990.7  730.32  1010.9  735.04    1112  781.84
  1344.1  861.39  1475.3  877.38    1556  878.87  1697.2  878.35  1838.5  874.87
#Mann= 3 , 0 , 0
       0      .1       0   907.4    .045       0   932.4     .06       0
Bank Sta=907.4,932.4
XS Rating Curve= 0 ,0
Exp/Cntr=0.3,0.1

Type RM Length L Ch R = 1 ,19167.5 ,295.3,336.4,377.8
XS GIS Cut Line= 4
     1584517.694      415983.648     1584654.167      416701.949
     1584929.463      417164.054     1585136.474      417780.886
#Sta/Elev= 30
    10.2  996.56    81.2  992.47   182.8  994.88   203.1  992.68     264  965.29
   335.1  935.82   538.2  867.16   639.8  821.03     721   789.3   832.6  737.89
   842.8  734.44   852.9  733.75   883.4  736.68   913.8  729.45     995  726.27
    1013  724.36  1025.5  723.88 1030.92  726.11  1035.6   728.2  1066.1  750.59
  1106.7  777.64  1177.7     808  1299.1  871.03  1319.1  877.12  1429.2  880.42
  1489.3  875.59  1579.4  865.69  1749.5  866.33  1819.6  859.41  1919.7  846.37
#Mann= 3 , 0 , 0
    10.2     .06       0    1013    .045       0 1030.92     .06       0
Bank Sta=1013,1030.92
XS Rating Curve= 0 ,0
Exp/Cntr=0.3,0.1

Type RM Length L Ch R = 1 ,18831.1 ,279.3,253.2,227.1
XS GIS Cut Line= 5
     1584487.343      415993.378     1584494.824      416096.883
     1584640.591       416947.02     1584404.913      417138.929
     1584477.191      417852.294
#Sta/Elev= 30
     9.4 1007.86   134.2 1006.72   164.7 1001.21   306.7  949.39   418.3  913.53
   489.4   888.1     530  870.39   611.2  831.51   743.1  784.74   844.5  733.91
   854.7  730.56   905.4  734.61     946  728.27   986.6  727.08  1047.4  728.38
  1095.7  723.03  1108.2  721.54  1120.7  722.05  1179.1  735.66  1270.2  773.31
  1320.7  788.76  1340.9  792.48  1371.2  795.43  1401.5  795.96  1462.1  791.99
  1482.3  792.57  1684.3  817.29  1775.2  819.07  1946.9  833.76  1987.3  835.16
#Mann= 3 , 0 , 0
       0     .06       0  1095.7    .045       0  1120.7     .06       0
Bank Sta=1095.7,1120.7
XS Rating Curve= 0 ,0
Exp/Cntr=0.3,0.1

Type RM Length L Ch R = 1 ,18577.9 ,338.7,335.8,334.3
XS GIS Cut Line= 4
     1584480.802      415985.102     1584350.448      416600.262
     1584370.112      417082.031     1584202.427      417877.249
#Sta/Elev= 30
    10.1 1011.49    81.1 1014.98   111.6 1008.38   223.1  969.36   365.1  907.26
   436.1  883.64     568  843.89   628.8  817.85   759.4  775.34   839.8   742.5
   869.9  733.05   897.6  720.78   910.1  719.87   922.6  721.69   990.4  731.94
  1050.7   736.1  1070.8  739.54  1171.9   782.1  1202.4  792.87  1243.1  802.22
  1283.7  804.67  1293.8  808.52  1314.2  821.38  1354.8  838.16  1436.1  856.85
    1558  894.07  1618.9  909.38  1679.9   919.5  1791.6   928.6  1923.7   927.8
#Mann= 3 , 0 , 0
       0      .1       0   897.6    .045       0   922.6      .1       0
Bank Sta=897.6,922.6
XS Rating Curve= 0 ,0
Exp/Cntr=0.3,0.1

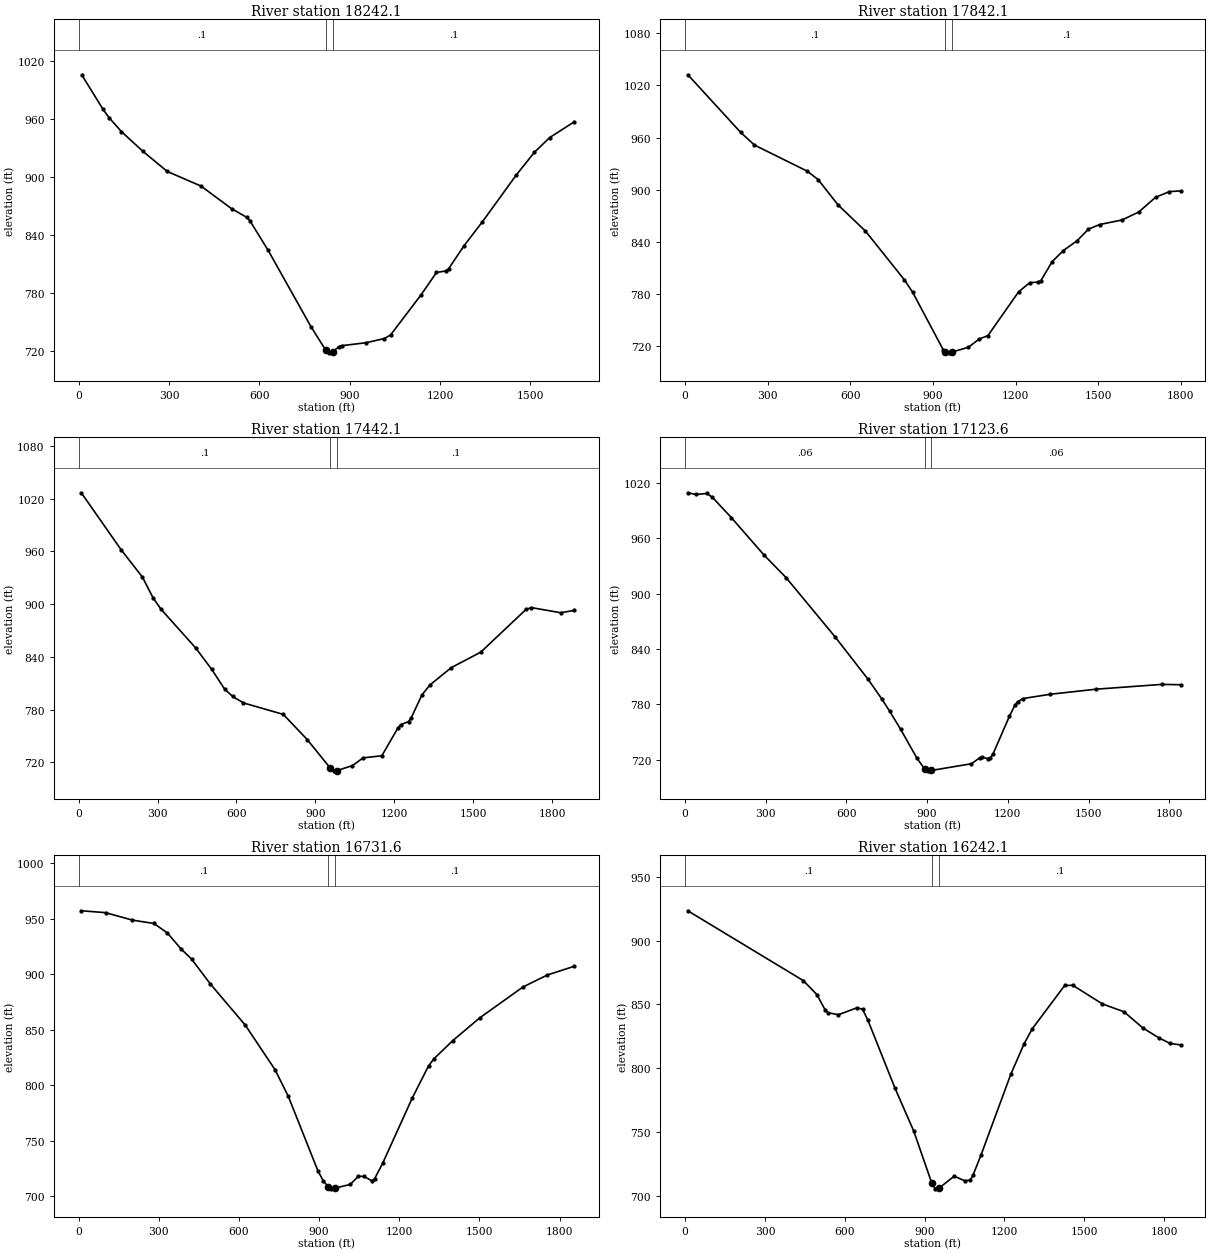
Type RM Length L Ch R = 1 ,18242.1 ,398.3,400,401.8
XS GIS Cut Line= 3
     1583906.934      416082.533     1584030.226      416906.114
     1584113.406      417714.646
#Sta/Elev= 30
    10.2 1005.82    81.2  970.01   101.6  961.23   142.2  946.97   213.3  926.62
   294.5  905.72   406.2  890.67   507.8  867.26   558.6  858.22   568.7  854.76
   629.6  823.97   771.8  744.94   820.3  720.91   832.8     718   845.3  719.29
   863.2  724.14   873.4  725.38   954.7  728.47  1015.6  732.83    1036  736.55
  1137.6  778.23  1188.4   801.2  1218.8  802.69    1229  805.19  1279.8  828.85
  1340.8  853.61  1452.5  901.74  1513.5   925.6  1564.3  940.83  1645.6  957.08
#Mann= 3 , 0 , 0
       0      .1       0   820.3    .045       0   845.3      .1       0
Bank Sta=820.3,845.3
XS Rating Curve= 0 ,0
Exp/Cntr=0.3,0.1

Type RM Length L Ch R = 1 ,17842.1 ,392,400,407.1
XS GIS Cut Line= 3
     1583576.966      416095.463     1583654.078      417039.667
     1583680.798      417891.622
#Sta/Elev= 30
    10.1 1032.33   201.6  966.11     252  951.46   443.4  921.48   483.8  911.56
   554.3  883.02   655.1  852.45   796.2  796.54   826.4  782.14   937.3  716.06
     945  713.61   957.5  712.44     970   713.4  1028.5  718.81  1069.1  728.52
  1099.6  732.17  1211.2  782.61  1251.8   793.2  1282.2  793.79  1292.4   795.6
  1332.9  817.29  1373.5  830.04  1424.3  841.59  1464.9  854.74  1505.4  860.04
  1586.6  865.24  1647.5  874.44  1708.4  891.32  1759.1  897.92  1799.7  898.76
#Mann= 3 , 0 , 0
       0      .1       0     945    .045       0     970      .1       0
Bank Sta=945,970
XS Rating Curve= 0 ,0
Exp/Cntr=0.3,0.1

Type RM Length L Ch R = 1 ,17442.1 ,318.9,318.6,317.4
XS GIS Cut Line= 3
     1583460.929      416091.924     1583258.118      417040.496
      1583051.55       417930.95
#Sta/Elev= 30
    10.1 1026.61   161.7  961.73   242.5  930.75   282.9  907.15   313.2  894.14
   444.6  850.26   505.2  826.06   555.7  803.05     586  794.88   626.5  787.57
     778  774.54     869  745.94   957.5  713.17     970  710.31   982.5  710.66
  1041.1  716.25  1081.7   725.1  1152.8  727.45  1213.8  758.99  1223.9  762.63
  1254.4  766.42  1264.6  770.66  1305.2  796.67  1335.7     808  1416.9  827.73
  1528.6  845.25  1701.3  893.98  1721.6  895.99  1833.3  890.14  1884.1  892.82
#Mann= 3 , 0 , 0
       0      .1       0   957.5    .045       0   982.5      .1       0
Bank Sta=957.5,982.5
XS Rating Curve= 0 ,0
Exp/Cntr=0.3,0.1

Type RM Length L Ch R = 1 ,17123.6 ,386.8,391.9,397.4
XS GIS Cut Line= 3
     1583175.956      416015.984     1582988.937       416909.65
     1582815.582      417822.798
#Sta/Elev= 30
    10.1 1009.03    40.6 1007.19    81.2 1008.26   101.4 1004.19   172.5  981.96
   294.2  941.42   375.4  917.23     558  852.96   679.7  807.39   730.4  786.27
   760.9  772.43   801.4  753.03   862.3  721.59   890.4  710.17   902.9  708.05
   915.4  708.46  1064.6  715.72  1094.9  722.04    1105  722.72  1125.2  721.36
  1135.3  722.03  1145.4  726.63    1206  767.21  1226.2  779.05  1236.3  782.89
  1256.5  786.31  1357.5  790.94  1529.3  796.46  1771.8  801.61  1842.5  801.28
#Mann= 3 , 0 , 0
       0     .06       0   890.4    .045       0   915.4     .06       0
Bank Sta=890.4,915.4
XS Rating Curve= 0 ,0
Exp/Cntr=0.3,0.1

Type RM Length L Ch R = 1 ,16731.6 ,478.3,489.5,497.3
XS GIS Cut Line= 3
     1582985.332      415961.169     1582618.941      416800.269
     1582259.223      417667.299
#Sta/Elev= 30
    10.1   957.2   100.6  955.52   201.2  948.81   281.7  945.76     332  937.24
   382.3  923.09   422.6   913.7     493  891.23   623.8   854.1   734.5  814.19
   784.8  789.91   895.5  722.82   915.6  713.85   933.4  708.68   945.9  706.68
   958.4  707.25  1016.5  710.67  1046.8  717.95    1067   717.9  1097.3  713.92
  1107.4   715.7  1137.7  729.74  1248.7  788.62  1309.2   817.4  1329.4  823.81
  1400.1  840.25    1501  860.73  1662.5   888.5  1753.4  899.31  1854.3  907.17
#Mann= 3 , 0 , 0
       0      .1       0   933.4    .045       0   958.4      .1       0
Bank Sta=933.4,958.4
XS Rating Curve= 0 ,0
Exp/Cntr=0.3,0.1

Type RM Length L Ch R = 1 ,16242.1 ,168.4,168.8,172.5
XS GIS Cut Line= 3
     1582892.878      415890.345      1582221.49      416547.993
     1581645.169       417267.82
#Sta/Elev= 30
    10.1  923.41   444.6  868.58   495.2  857.66   525.5  845.89   535.6  843.55
     576  841.87   646.8  847.38     667  846.07   687.2  837.41   788.2  784.47
     859  750.68   927.3  709.52   939.8   705.3   952.3  705.57  1010.8  715.19
  1051.3   711.6  1071.6  712.21  1081.7  715.94  1112.1  731.96  1223.5  795.02
  1274.2   819.3  1304.6  830.89  1426.2   864.8  1456.6  864.97  1568.1  850.33
  1649.1  844.18  1720.1  831.48  1780.9  823.63  1821.4  819.46  1861.9  818.16
#Mann= 3 , 0 , 0
       0      .1       0   927.3    .045       0   952.3      .1       0
Bank Sta=927.3,952.3
XS Rating Curve= 0 ,0
Exp/Cntr=0.3,0.1

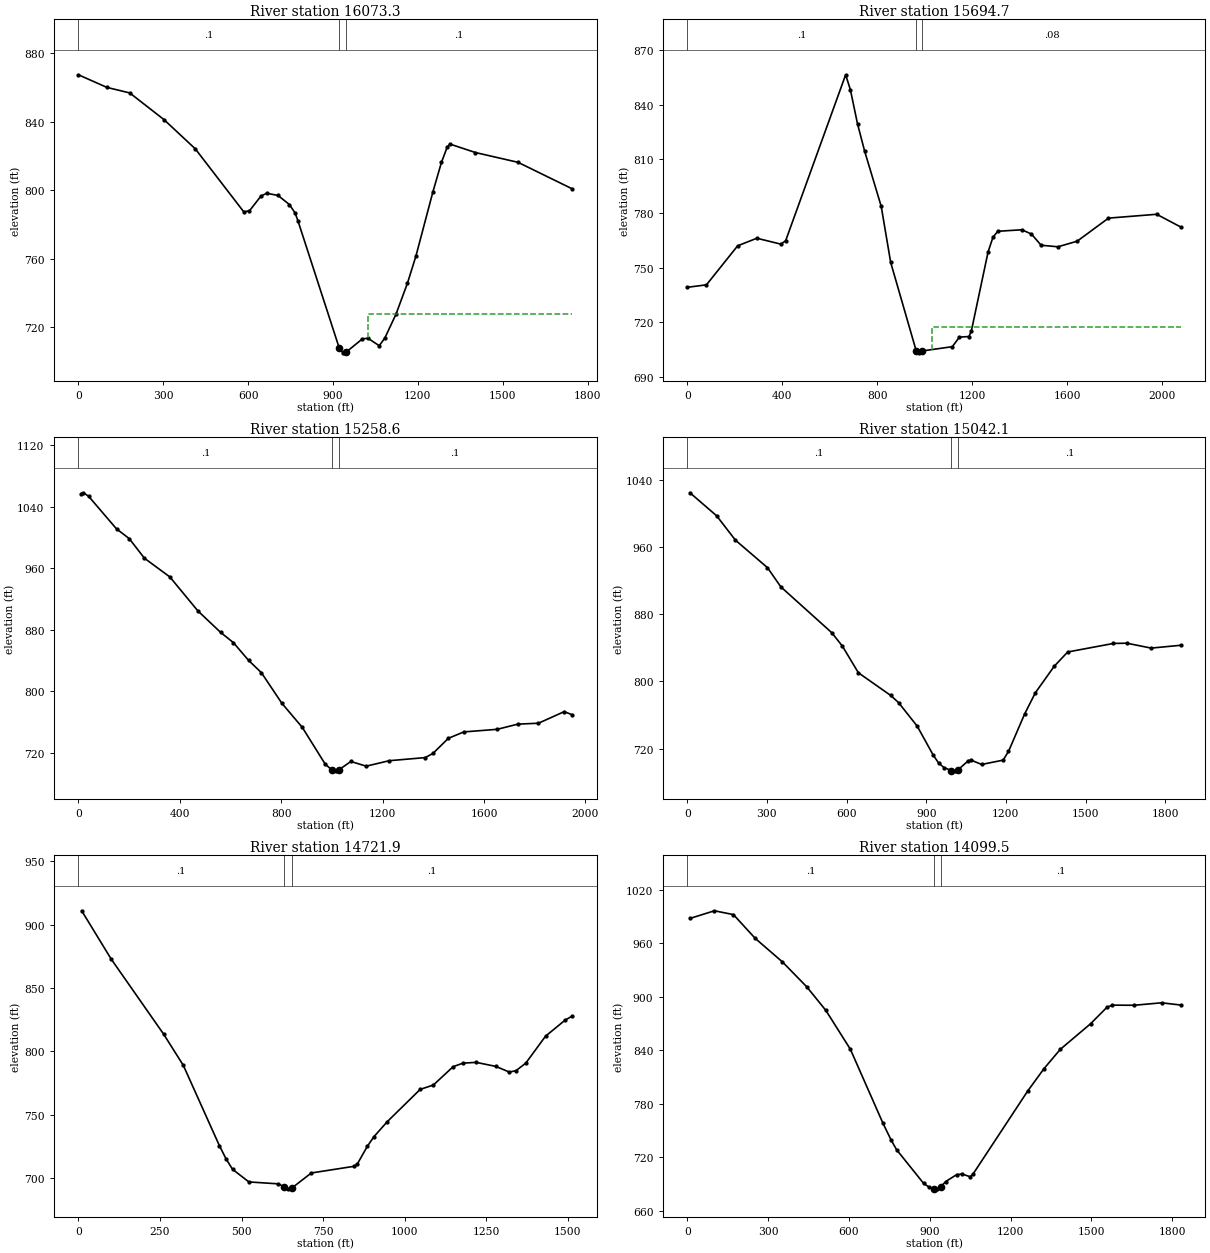
Type RM Length L Ch R = 1 ,16073.3 ,421.6,378.6,335.3
XS GIS Cut Line= 4
     1582802.286      415786.317     1582200.885      416338.513
     1581998.595      416527.135     1581648.689      417076.597
#Sta/Elev= 30
       0  867.29   100.8  859.93   181.4  856.71   302.4  841.17   413.3   824.1
   584.6  787.38   604.8  787.98   645.1  796.52   665.3   798.2   705.6  796.95
   745.9  791.63   766.1   786.7   776.1  782.15   922.5  707.79     935  705.18
   947.5  705.73  1004.1  713.34  1023.9  713.66  1063.4  709.34  1083.2  713.77
  1123.1  727.86  1163.2  745.77  1193.3  761.67  1253.4  799.14  1283.5  816.27
  1303.5  825.03  1313.5  826.89  1403.7  821.95    1554  816.26  1744.5  800.89
#Mann= 3 , 0 , 0
       0      .1       0   922.5    .045       0   947.5      .1       0
#XS Ineff= 2 , 0
                         1022.21          727.68
Permanent Ineff=
       F       F
Bank Sta=922.5,947.5
XS Rating Curve= 0 ,0
Exp/Cntr=0.3,0.1

Type RM Length L Ch R = 1 ,15694.7 ,454,436.1,418
XS GIS Cut Line= 4
     1582596.133       415564.06     1581995.862      415854.658
     1581802.885      416357.829     1581567.364      417197.426
#Sta/Elev= 30
       0  739.22    80.8  740.58   212.2  762.12     293  766.28   394.1  763.03
   414.3  764.93   666.9  856.45   686.9  848.17   716.8  829.39   746.8  814.33
   816.6  783.89   856.5  752.95   963.8  704.25   976.3  703.07   988.8   704.1
    1116  706.47  1145.9  711.73  1185.9  712.08  1195.8   714.9  1266.7  758.79
  1286.9  766.72  1307.2  770.12  1408.6  770.95  1449.2   768.6  1489.7  762.44
  1560.7  761.56  1641.8  764.66  1773.6  777.38  1976.4   779.5  2077.8  772.48
#Mann= 3 , 0 , 0
       0      .1       0   963.8    .045       0   988.8     .08       0
#XS Ineff= 2 , 0
                         1028.56          717.08
Permanent Ineff=
       F       F
Bank Sta=963.8,988.8
XS Rating Curve= 0 ,0
Exp/Cntr=0.3,0.1

Type RM Length L Ch R = 1 ,15258.6 ,209.1,216.5,223.8
XS GIS Cut Line= 4
     1581477.525      415258.903     1581399.772      415905.557
     1581566.917      416465.981     1581465.757      417169.338
#Sta/Elev= 30
      10 1056.82      20 1058.12    40.1 1053.62   150.3 1011.19   200.4  998.56
   260.5     973   360.7   948.7   470.9  904.67   561.1  876.54   611.2  863.33
   671.5   840.1   721.9  824.18   802.6  784.38   883.2  753.04     974  705.06
  1001.8  697.21  1014.3  696.52  1026.8  697.67  1074.8   708.7  1135.3  702.59
    1226  709.69  1368.1  713.75  1398.6  719.15  1459.5  738.85  1520.4  747.13
  1652.3  750.53  1733.5  757.26  1814.8  758.43  1916.3  773.48  1946.7  769.64
#Mann= 3 , 0 , 0
       0      .1       0  1001.8    .045       0  1026.8      .1       0
Bank Sta=1001.8,1026.8
XS Rating Curve= 0 ,0
Exp/Cntr=0.3,0.1

Type RM Length L Ch R = 1 ,15042.1 ,309.6,320.3,330.6
XS GIS Cut Line= 3
     1581271.956      415276.308     1581291.414      416283.299
     1581311.284      417134.557
#Sta/Elev= 30
    10.1 1024.35   110.8  996.92   181.3  968.03   302.2  935.26   352.5  912.45
   543.9  858.05   584.2  842.02   644.6  810.26   765.5  783.49   795.7  774.88
   866.2  746.74   926.6  712.25   946.7  702.99   966.9  697.53   994.7  693.95
  1007.2  693.65  1019.7  694.82  1057.9   705.5    1068  706.58  1108.5  701.24
  1189.6  706.36  1209.9  716.69  1270.7  761.26  1311.3   786.6  1382.2  818.05
  1432.9  834.99  1605.2  845.17  1655.9  845.45  1747.2  839.62  1858.7  842.98
#Mann= 3 , 0 , 0
       0      .1       0   994.7    .045       0  1019.7      .1       0
Bank Sta=994.7,1019.7
XS Rating Curve= 0 ,0
Exp/Cntr=0.3,0.1

Type RM Length L Ch R = 1 ,14721.9 ,632.5,622.3,614
XS GIS Cut Line= 3
     1581222.796      415600.764     1580990.999      416200.526
     1580691.868      417016.573
#Sta/Elev= 30
      10  910.88   100.5  872.77   261.2  813.55   321.5  788.94     432  725.62
   452.1  715.36   472.2  706.98   522.4     697   612.9  695.48   630.5  693.05
     643  691.55   655.5  692.48   713.7  704.06   845.1  709.34   855.2  711.37
   885.5  725.18   905.8  732.75   946.2  744.48  1047.2  769.98  1087.7  773.44
  1148.3  787.92  1178.6  790.71  1219.1   791.3  1279.7  788.08  1320.1  783.68
  1340.3  784.67  1370.7  790.65  1431.3  811.93  1491.9  824.74  1512.1  827.65
#Mann= 3 , 0 , 0
       0      .1       0   630.5    .045       0   655.5      .1       0
Bank Sta=630.5,655.5
XS Rating Curve= 0 ,0
Exp/Cntr=0.3,0.1

Type RM Length L Ch R = 1 ,14099.5 ,259.3,257.4,256.7
XS GIS Cut Line= 3
     1580523.154      415067.074     1580524.724      415944.885
     1580495.228      416898.589
#Sta/Elev= 30
    10.1  987.81   100.9  996.39   171.5  992.09   252.2  965.46   353.1  939.11
     444  910.98   514.6   884.6   605.4  841.18   726.5  758.12   756.7  739.37
   776.9  728.51   877.8  690.55   898.1  686.44   916.1   684.9   928.6  684.56
   941.1  686.85     959  692.67   999.6  700.39  1019.9  701.18  1050.4  698.14
  1060.5  700.95  1263.5  794.12  1324.4  819.38  1385.3  841.13    1497  869.62
  1557.9  888.15  1578.2  890.57  1659.4  890.43  1760.9   893.2    1832  890.68
#Mann= 3 , 0 , 0
       0      .1       0   916.1    .045       0   941.1      .1       0
Bank Sta=916.1,941.1
XS Rating Curve= 0 ,0
Exp/Cntr=0.3,0.1