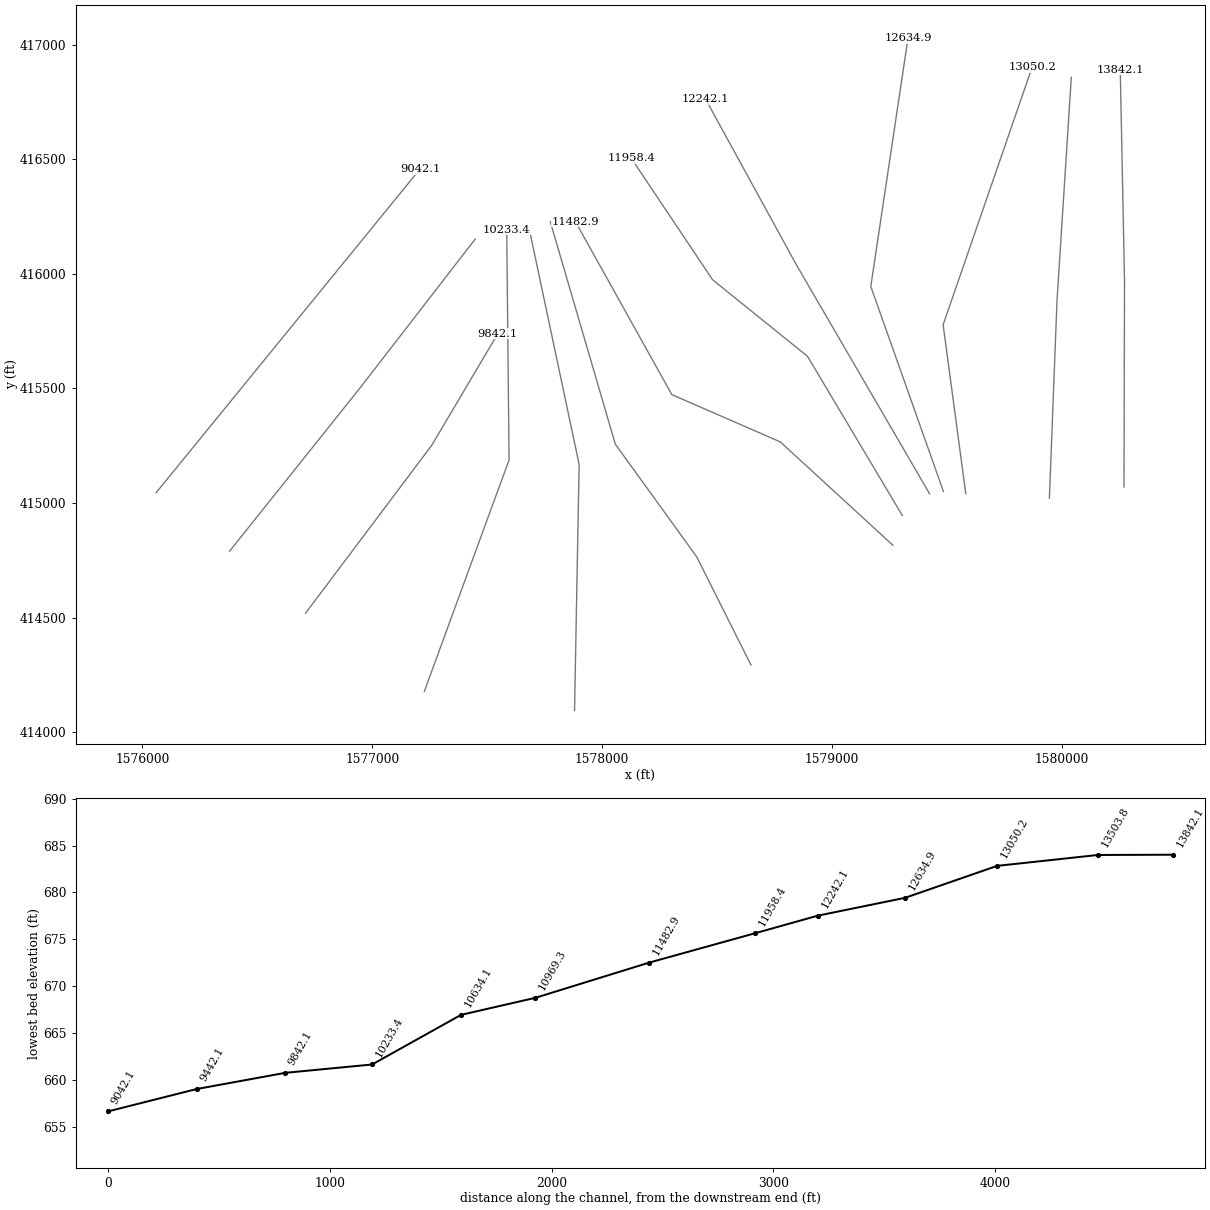
HEC-RAS study LAURELCR.prj: LAURELCR

--- LAURELCR.g01 (geometry) --- (continued)

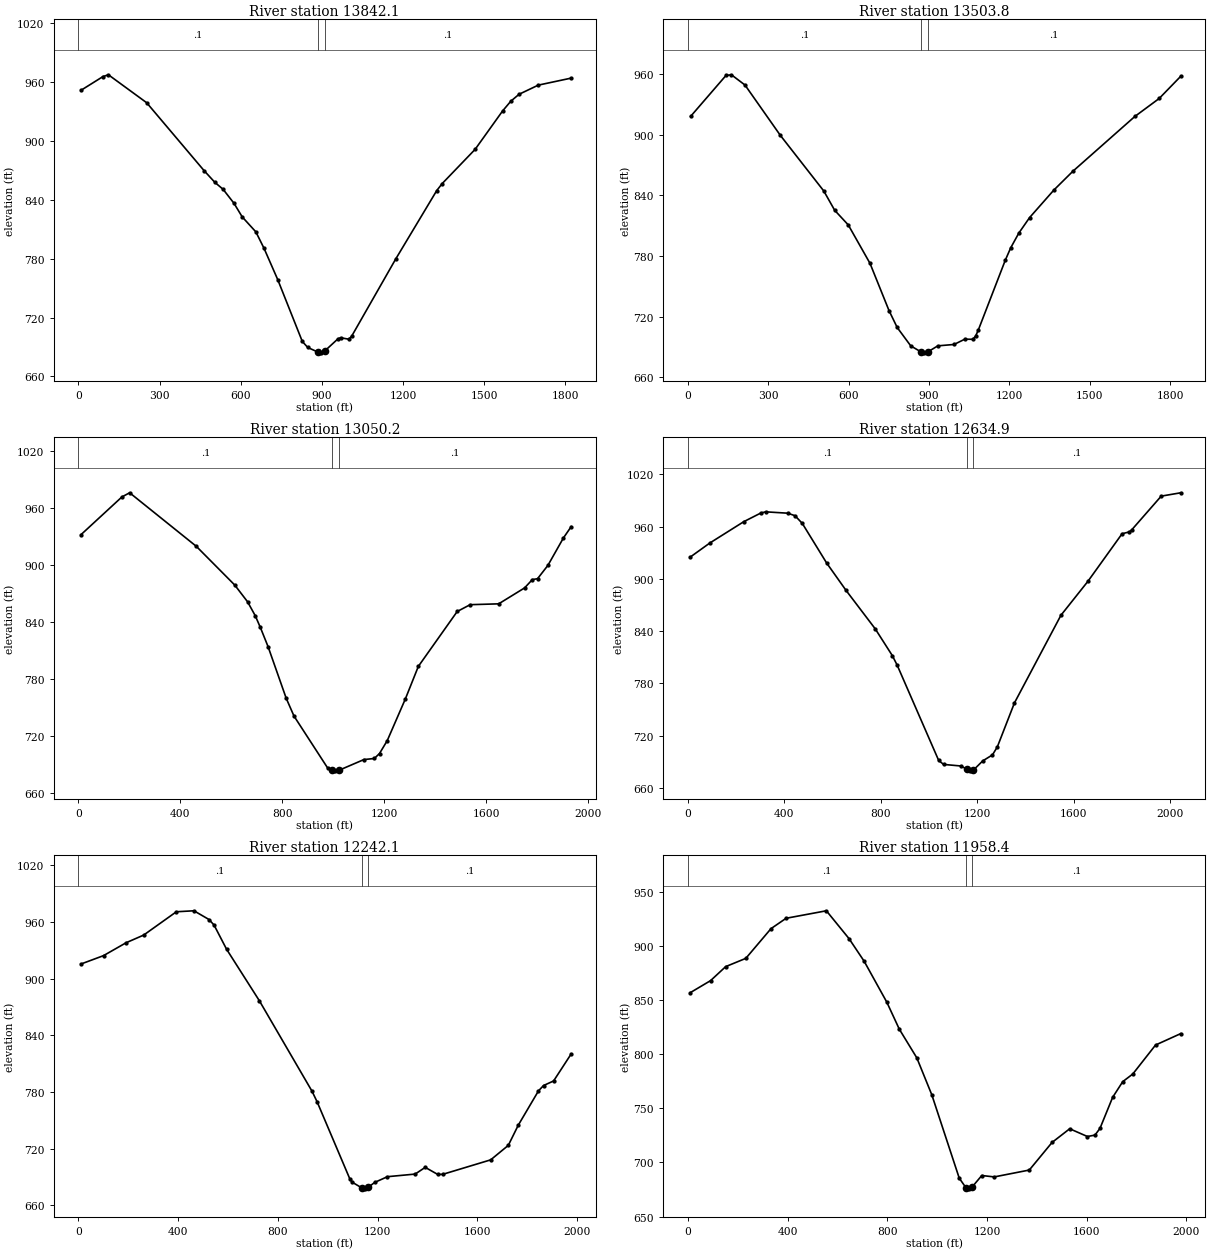
Type RM Length L Ch R = 1 ,13842.1 ,340.7,338.4,331.8
XS GIS Cut Line= 3
     1580269.092      415069.836     1580271.387      415968.049
     1580252.873      416891.197
#Sta/Elev= 30
    10.1  951.77    90.8  965.68     111  967.52   252.3  939.05   464.2  869.92
   504.6  857.79   534.9  850.76   575.3  836.43   605.5  822.63     656  807.34
   686.3  790.51   736.7  758.74   827.6  695.66   847.8  689.48   885.7  684.75
   898.2  684.02   910.7  685.95   959.1  698.24   969.2  699.38   999.7  697.93
  1009.8  700.87  1172.2  779.39  1324.4  849.43  1344.7  856.62  1466.4  891.52
  1567.9  930.65  1598.3  940.59  1628.8  947.65  1699.8  956.97  1821.5  964.13
#Mann= 3 , 0 , 0
       0      .1       0   885.7    .045       0   910.7      .1       0
Bank Sta=885.7,910.7
XS Rating Curve= 0 ,0
Exp/Cntr=0.3,0.1

Type RM Length L Ch R = 1 ,13503.8 ,461.5,453.6,448.9
XS GIS Cut Line= 3
     1579944.635      415020.676      1579977.71      415882.129
     1580039.899        416857.4
#Sta/Elev= 30
    10.1  918.38     142  958.93   162.3  959.62     213  949.45   344.8  899.61
   507.1   844.4   547.7   825.3   598.4  810.79   679.5   772.7   750.5  725.86
     781  709.11   831.7  690.86   869.7  684.96   882.2  683.99   894.7  684.82
   932.6  690.92   993.1  692.28  1033.4  697.54  1063.6  697.41  1073.7  700.64
  1083.7  706.57  1184.5  775.86  1204.6  788.06  1234.9  802.69  1275.2  818.09
  1365.8  845.38  1436.3  863.91  1668.1  918.34  1758.7  936.12  1839.3  958.16
#Mann= 3 , 0 , 0
       0      .1       0   869.7    .045       0   894.7      .1       0
Bank Sta=869.7,894.7
XS Rating Curve= 0 ,0
Exp/Cntr=0.3,0.1

Type RM Length L Ch R = 1 ,13050.2 ,409.2,415.3,420.8
XS GIS Cut Line= 3
     1579581.035      415040.294     1579482.531      415777.741
     1579869.605      416901.909
#Sta/Elev= 30
    10.1  931.38   170.9  971.17   201.1  975.51   462.5  919.16   613.3  878.38
   663.6  860.77   693.7   846.1   713.8  833.73     744  813.53   815.1  759.21
   845.6   740.5   977.7  685.79   995.7  683.35  1008.2  682.83  1020.7  683.26
    1120  694.71  1160.6  695.82    1181  701.06  1211.4  714.66  1282.6  758.65
  1333.4  792.81  1485.8  850.57  1536.6  857.72  1648.4  858.61    1750  875.38
  1780.5  884.16  1800.8  885.07  1841.5  899.11  1902.5  928.07  1932.9  939.92
#Mann= 3 , 0 , 0
       0      .1       0   995.7    .045       0  1020.7      .1       0
Bank Sta=995.7,1020.7
XS Rating Curve= 0 ,0
Exp/Cntr=0.3,0.1

Type RM Length L Ch R = 1 ,12634.9 ,375.3,392.8,410.1
XS GIS Cut Line= 3
     1579483.779       415050.31     1579167.907      415944.885
     1579329.713      417028.365
#Sta/Elev= 30
    10.1  925.02    90.8  941.06   232.1  965.65   302.8  975.58     323  976.88
   413.8  975.33   444.1  972.45   474.4  963.59   575.3  918.14     656  886.62
   777.1  842.42   847.8  811.76     868  800.75    1040  691.41  1060.3   686.8
  1131.3  685.01  1159.4  681.11  1171.9  679.42  1184.4  680.37  1222.6  690.79
  1263.2  697.76  1283.4  706.95  1354.4  757.48  1547.2  858.11  1658.7  896.95
  1800.8  951.74  1831.2  953.86  1841.3  956.36  1963.1  994.92  2044.2  998.77
#Mann= 3 , 0 , 0
       0      .1       0  1159.4    .045       0  1184.4      .1       0
Bank Sta=1159.4,1184.4
XS Rating Curve= 0 ,0
Exp/Cntr=0.3,0.1

Type RM Length L Ch R = 1 ,12242.1 ,273.5,283.7,294.7
XS GIS Cut Line= 3
     1579423.539       415040.34     1578847.191      416034.303
      1578450.17      416760.941
#Sta/Elev= 30
    10.1  915.31   100.8   924.2   191.5  937.85     262  945.96   393.1  970.62
   463.6  971.66   524.1   962.4   544.3  956.54   594.6  930.94   725.7  876.63
   937.3  780.75   957.5  769.69  1088.5  688.29  1098.6  684.52  1136.5  678.58
    1149  677.52  1161.5  679.02  1189.4  684.41  1239.9  690.38  1350.9  693.13
  1391.3  700.24  1441.8  692.72    1462   692.9  1653.9  708.18  1724.6   723.5
  1764.9  745.02  1845.7  781.16  1865.9  786.79  1906.3  791.64    1977   820.3
#Mann= 3 , 0 , 0
       0      .1       0  1136.5    .045       0  1161.5      .1       0
Bank Sta=1136.5,1161.5
XS Rating Curve= 0 ,0
Exp/Cntr=0.3,0.1

Type RM Length L Ch R = 1 ,11958.4 ,468.1,475.5,483
XS GIS Cut Line= 4
     1579305.211      414945.324     1578892.611      415640.092
     1578479.666      415974.381     1578125.714      416505.309
#Sta/Elev= 30
    10.1     857    90.9  868.03   151.5  880.97   232.3  888.61   333.3  916.05
   393.9  925.64   555.5  932.57   646.4  906.83     707  885.97   797.9  848.16
   848.1  823.18   918.3  796.69   978.5  762.54  1088.7  685.44  1116.3  676.43
  1128.8  675.64  1141.3  677.63    1179  687.95  1229.1  686.66  1369.7  693.01
  1460.9  718.49  1531.8  731.15  1602.7     724  1633.1  725.29  1653.3  731.53
    1704  760.17  1744.5  774.67    1785  781.77  1876.2  808.52  1977.4  819.09
#Mann= 3 , 0 , 0
       0      .1       0  1116.3    .045       0  1141.3      .1       0
Bank Sta=1116.3,1141.3
XS Rating Curve= 0 ,0
Exp/Cntr=0.3,0.1

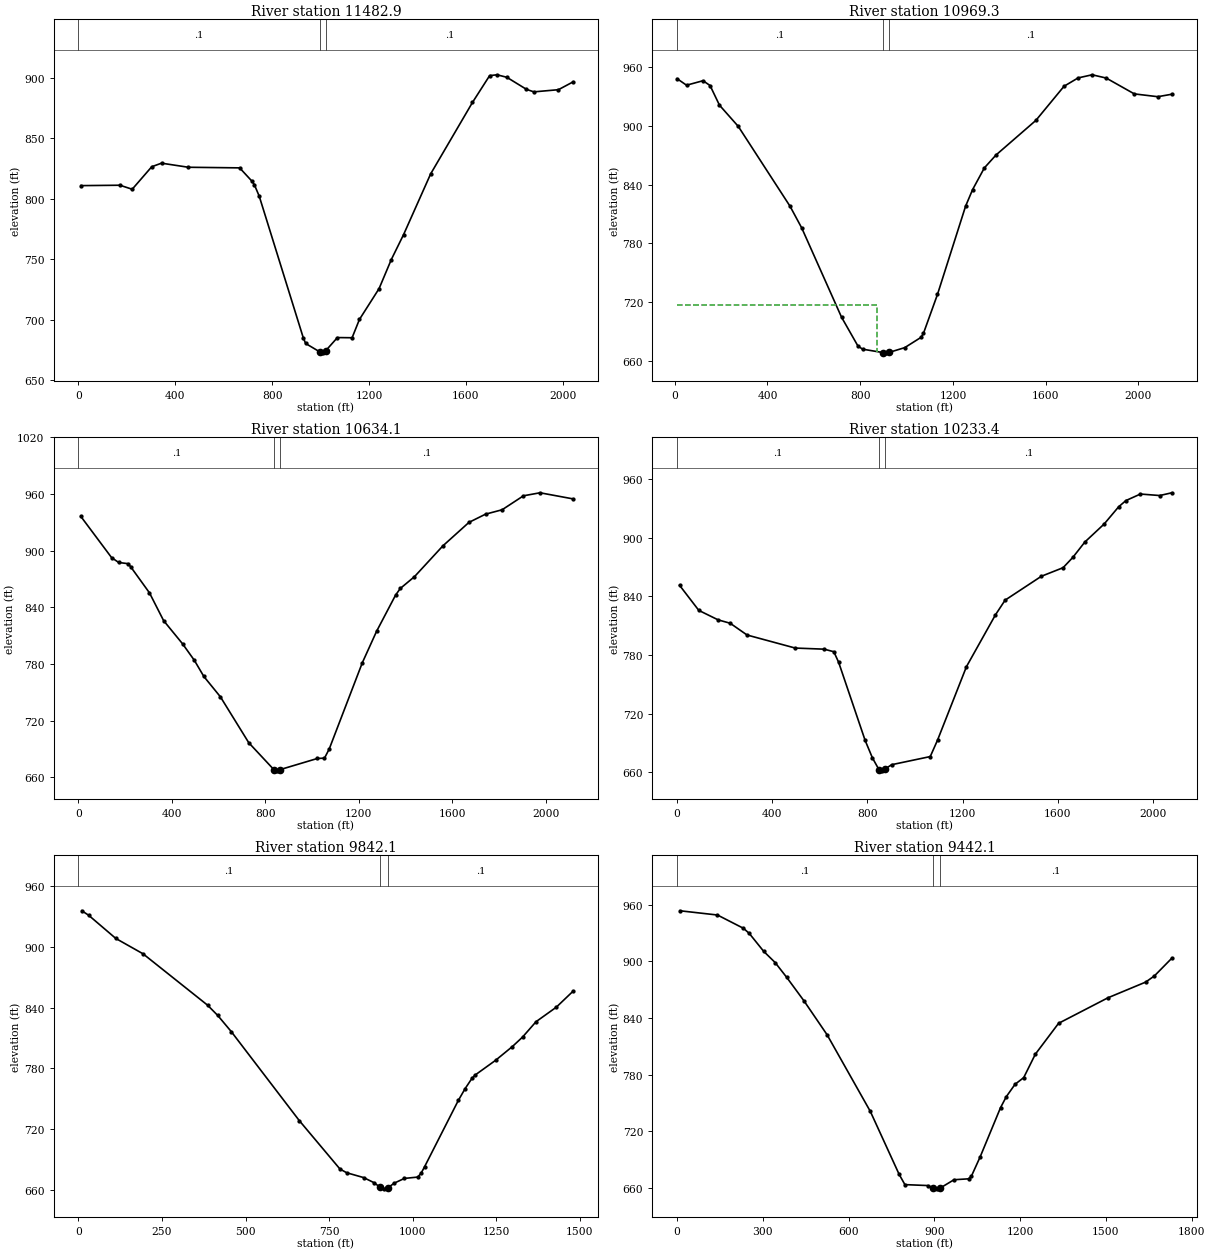
Type RM Length L Ch R = 1 ,11482.9 ,530,513.6,497.8
XS GIS Cut Line= 4
     1579264.419      414815.266     1578774.627      415266.476
      1578302.69      415472.948     1577883.639      416227.273
#Sta/Elev= 30
    10.1  810.69   171.5  811.01     222  807.69   302.7  826.29   343.1  829.24
   454.1  825.86   665.9  825.36   716.5  814.43   726.6  811.51   746.8  802.02
   928.6  685.15   938.7  680.25   996.9  673.33  1009.4  672.52  1021.9  674.34
    1070  685.14  1130.6  684.99  1160.9   700.1    1242  725.57  1292.7  749.64
  1343.5  770.29  1455.2  820.39  1627.8  879.38  1698.8  901.55  1729.3  902.28
  1769.9  900.21  1851.1  890.24  1881.6  888.16  1983.1  889.95    2044  896.45
#Mann= 3 , 0 , 0
       0      .1       0   996.9    .045       0  1021.9      .1       0
Bank Sta=996.9,1021.9
XS Rating Curve= 0 ,0
Exp/Cntr=0.3,0.1

Type RM Length L Ch R = 1 ,10969.3 ,353.4,335.2,315.6
XS GIS Cut Line= 4
     1578646.811      414293.107     1578410.842      414765.044
      1578056.89      415256.644     1577774.047      416227.505
#Sta/Elev= 30
    10.1  947.63    50.7  941.02   121.8  945.59   152.2  940.69   192.8  920.71
     274  899.11   497.2  817.92   547.8  795.76   719.5  705.02   790.1  675.76
   810.3  672.49   898.8  669.01   911.3  668.76   923.8  669.14   992.1  674.04
  1062.7  684.54  1072.8  688.46  1133.4  728.14  1254.8  817.99  1285.1  834.87
  1335.7  856.89  1386.2  870.06  1558.1  905.23  1679.5  939.94  1740.1  948.43
  1800.8  951.63  1861.5  948.29  1982.8  932.18    2084  929.33  2144.6  931.84
#Mann= 3 , 0 , 0
    10.1      .1       0   898.8    .045       0   923.8      .1       0
#XS Ineff= 2 , 0
          872.37  716.92
Permanent Ineff=
       F       F
Bank Sta=898.8,923.8
XS Rating Curve= 0 ,0
Exp/Cntr=0.3,0.1

Type RM Length L Ch R = 1 ,10634.1 ,409.7,400.7,391.7
XS GIS Cut Line= 3
     1577879.501      414094.587     1577899.578      415168.156
     1577683.742      416190.203
#Sta/Elev= 30
    10.1  936.15   141.8  892.57   172.2  887.42   212.7  886.13   222.9   883.1
   303.9  855.33   364.7  825.84   445.7  801.37   496.4  783.81   536.9  766.79
   607.8  745.25   729.3  696.66   838.4  667.78   850.9  666.94   863.4  668.24
  1023.1  680.03  1053.5  680.38  1073.8  690.08  1215.7  781.45  1276.6  814.61
  1357.7   852.8    1378  859.89  1438.9  872.42  1560.6  905.03  1672.1  929.84
  1743.1  938.53  1814.1  943.18  1905.4  957.96  1976.4  961.16  2118.3  954.67
#Mann= 3 , 0 , 0
       0      .1       0   838.4    .045       0   863.4      .1       0
Bank Sta=838.4,863.4
XS Rating Curve= 0 ,0
Exp/Cntr=0.3,0.1

Type RM Length L Ch R = 1 ,10233.4 ,400.5,391.3,385.1
XS GIS Cut Line= 3
     1577226.536      414178.455     1577594.786       415187.82
       1577584.6       416193.29
#Sta/Elev= 30
    10.1  851.44    91.2  825.74   172.3  816.07     223  812.61     294  800.57
   496.7  787.22   618.3  786.09   658.9  783.47   679.1  772.67   790.6  692.71
     821  674.98   849.1  662.68   861.6  661.65   874.1  663.56   902.1  667.93
  1064.3  676.25  1094.8  692.99  1216.6  768.25  1338.5  821.23  1379.1  836.24
  1531.5  860.65  1622.9  869.42  1663.5  879.88  1714.3  895.66  1795.6  914.13
  1856.5  931.73    1887  938.07  1947.9  944.75  2029.2  943.22    2080  946.04
#Mann= 3 , 0 , 0
       0      .1       0   849.1    .045       0   874.1      .1       0
Bank Sta=849.1,874.1
XS Rating Curve= 0 ,0
Exp/Cntr=0.3,0.1

Type RM Length L Ch R = 1 ,9842.1  ,400.8,400,396.6
XS GIS Cut Line= 3
     1576709.905      414519.244     1577258.186      415251.163
     1577545.626      415738.413
#Sta/Elev= 30
    10.2  935.82    30.5  931.38   111.8  908.43   193.1  893.28   386.1  842.49
   416.6  832.32   457.3  816.27   660.5  728.35   782.4  680.37   802.7  676.66
   853.5  671.87     884   666.9     902  662.48   914.5  660.76     927  662.05
   944.8  666.39   975.1  671.06  1015.5  672.41  1025.6  676.46  1035.7  682.66
  1136.7  748.29    1157  759.92  1177.2  769.96  1187.3  773.43  1247.9  787.85
  1298.4  801.53  1328.7  810.86  1369.1  826.09  1429.7  840.43  1480.2  856.35
#Mann= 3 , 0 , 0
       0      .1       0     902    .045       0     927      .1       0
Bank Sta=902,927
XS Rating Curve= 0 ,0
Exp/Cntr=0.3,0.1

Type RM Length L Ch R = 1 ,9442.1  ,400.3,400,399.3
XS GIS Cut Line= 3
      1576379.39      414789.674     1576944.877      415499.833
     1577447.306      416151.357
#Sta/Elev= 30
    10.1  953.53   141.2  949.04     232  934.97   252.2  929.61   302.6  910.65
   342.9   898.7   383.3  883.03   443.8  858.11   524.5  822.27   675.8  741.08
   776.7  674.34   796.8   663.5   877.5   662.5   895.3  660.15   907.8  659.03
   920.3  659.87   968.7  668.68  1019.5  669.63  1029.7  672.59  1060.2  692.97
  1131.3  744.95  1151.6  756.66  1182.1  769.74  1212.5  776.85  1253.2  801.67
  1334.4  834.33  1507.1  861.37  1639.1     878  1669.6  884.53  1730.6   903.3
#Mann= 3 , 0 , 0
       0      .1       0   895.3    .045       0   920.3      .1       0
Bank Sta=895.3,920.3
XS Rating Curve= 0 ,0
Exp/Cntr=0.3,0.1

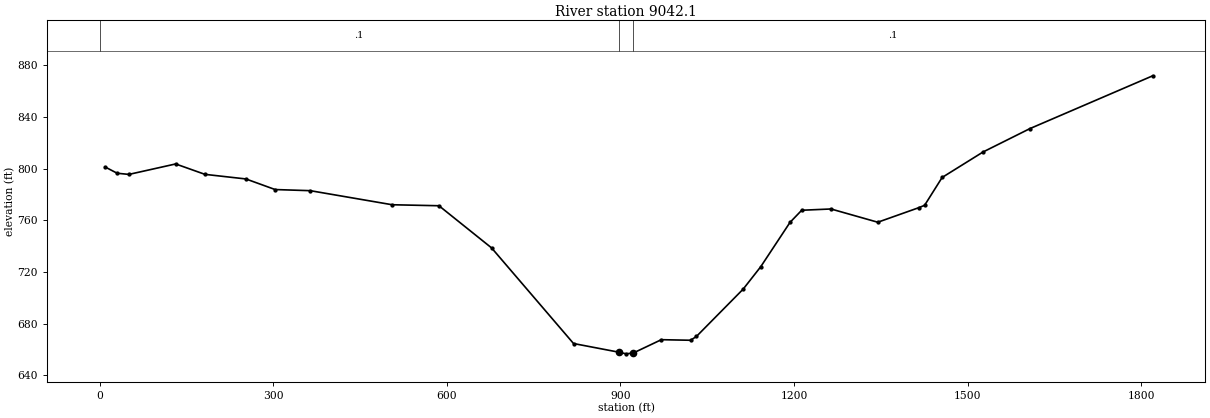
Type RM Length L Ch R = 1 ,9042.1  ,9046.199,9042.2,9037.801
XS GIS Cut Line= 3
     1576059.804      415044.737     1576633.599      415751.036
     1577207.395      416457.335
#Sta/Elev= 30
    10.1  801.09    30.3  796.39    50.6  795.49   131.4  803.58     182  795.53
   252.8  791.97   303.3  783.77     364   782.9   505.6  772.01   586.4  771.24
   677.4   738.6     819  664.62   897.5   657.9     910  656.64   922.5  657.34
   970.7  667.59  1021.2  667.15  1031.3  670.06  1112.2  706.75  1142.6  724.11
  1193.1  758.36  1213.3  767.75  1263.9  768.74  1344.8  758.48  1415.6  769.73
  1425.7  771.58    1456  793.13  1526.8  812.86  1607.7  830.93    1820  871.81
#Mann= 3 , 0 , 0
       0      .1       0   897.5    .045       0   922.5      .1       0
Bank Sta=897.5,922.5
XS Rating Curve= 0 ,0
Exp/Cntr=0.3,0.1

Chan Stop Cuts=-1
Use User Specified Reach Order=0